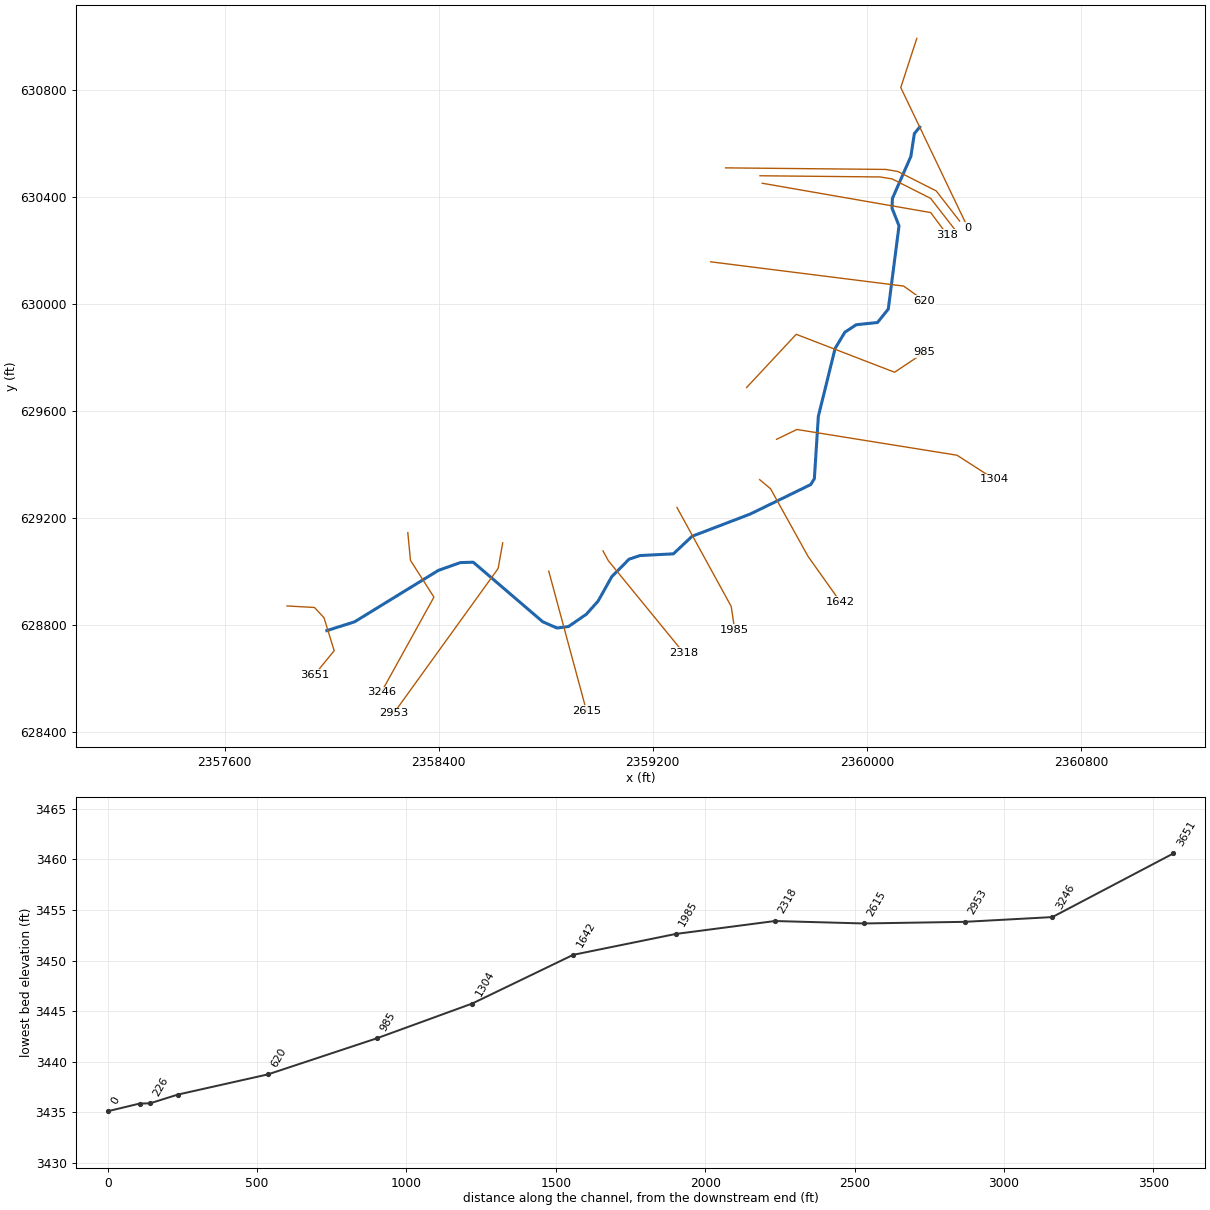
--- WARNERRN.prj (project) ---

Proj Title=WARNERRN
Current Plan=p01
Default Exp/Contr=0,0
English Units
Geom File=g01
Flow File=f01
Plan File=p01
BEGIN DESCRIPTION:
----------MODEL BY WOOD PLC 2022----------
AFH study
Randolph County, WV
HEC-RAS Version: RAS 6.2
Vertical Datum: NAVD88
Projection: NAD 1983 StatePlane West Virginia S FIPS 4702 (US Feet)
Terrain: 1-meter LIDAR (FEMA Region III 3DEP collected 2016-2018)
Land Use: 2019 NLCD
Hydrologic Method:
WV SIR2010-5033 regression equations
Additional Model Notes:
None
END DESCRIPTION:
DSS Export Rating Curves= 0
DSS Export Rating Curve Sorted= 0
DSS Export Volume Flow Curves= 0
DXF OffsetX= 0
DXF OffsetY= 0
DXF ScaleX= 0
DXF ScaleY= 0

--- WARNERRN.p01 (plan) ---

Plan Title=Floodplain
Program Version=6.20
Short Identifier=Floodplain
Geom File=g01
Flow File=f01
Subcritical Flow
K Sum by GR= 0
Std Step Tol= 0.01
Critical Tol= 0.01
Num of Std Step Trials= 20
Max Error Tol= 0.3
Flow Tol Ratio= 0.001
Split Flow NTrial= 30
Split Flow Tol= 0.02
Split Flow Ratio= 0.02
Log Output Level= 0
Friction Slope Method= 1
Unsteady Friction Slope Method= 2
Unsteady Bridges Friction Slope Method= 1
Parabolic Critical Depth
Global Vel Dist= 0 , 0 , 0
Global Log Level= 0
CheckData=True
Encroach Param=-1 ,0,0, 0
Mapping Interval=1HOUR
Computation Time Step Use Courant=        0
Computation Time Step Use Time Series=    0
Computation Time Step Count To Double=0
Computation Time Step Max Doubling=0
Computation Time Step Max Halving=0
Computation Time Step Residence Courant=0
Run HTab= 0
Run UNet= 0
Run Sediment= 0
Run PostProcess= 0
Run WQNet= 0
Run RASMapper=-1
UNET Theta= 0
UNET Theta Warmup= 0
UNET ZTol= 0
UNET ZSATol= 0
UNET MxIter= 0
UNET Max Iter WO Improvement= 0
UNET MaxInSteps= 0
UNET DtIC= 0
UNET DtMin= 0
UNET MaxCRTS= 0
UNET WFStab= 0
UNET SFStab= 0
UNET WFX= 1
UNET SFX= 1
UNET Gravity=32.174
UNET 1D Methodology=Finite Difference
UNET DSS MLevel= 1
UNET Pardiso=0
UNET DZMax Abort= 0
UNET Use Existing IB Tables= 0
UNET Froude Reduction=False
UNET Froude Limit= 0
UNET Froude Power= 0
UNET D1 Cores= 0
UNET WindReference=Eulerian
UNET WindDragFormulation=Hsu (1988)
UNET D2 Coriolis=0
UNET D2 Cores= 0
UNET D2 Theta= 1
UNET D2 Theta Warmup= 1
UNET D2 Z Tol= 0.01
UNET D2 Volume Tol= 0.01
UNET D2 Max Iterations= 20
UNET D2 Equation= 0
UNET D2 RampUpFraction=0.1
UNET D2 TimeSlices= 1
UNET D2 Turbulence Formulation=Non-Conservative (original)
UNET D2 Eddy Viscosity=0.3
UNET D2 Transverse Eddy Viscosity=0.1
UNET D2 Smagorinsky Mixing=0
UNET D2 BCVolumeCheck=0
UNET D2 Cores=0
UNET D2 SolverType=PARDISO (Direct)
UNET D2 Minimum Iterations= 2147483647
UNET D2 Maximum Iterations= 2147483647
UNET D2 Restart Number= 10
UNET D2 Relaxation Coeff=1.3
UNET D2 SOR Precondition Iterations= 10
UNET D2 ILUT Maximum Fill= 8
UNET D2 ILUT Tolerance=1E-08
UNET D1D2 MaxIter= 0
UNET D1D2 ZTol=0.01
UNET D1D2 QTol=0.1
UNET D1D2 MinQTol=1
Write IC File= 0
Write IC File at Fixed DateTime=0
Write IC File at Sim End=0
Echo Input=False
Echo Parameters=False
Echo Output=False
Write Detailed= 0
HDF Write Warmup=0
HDF Write Time Slices=0
HDF Flush=0
HDF Compression= 1
HDF Chunk Size= 1
HDF Spatial Parts= 1
HDF Use Max Rows=0
HDF Fixed Rows= 1
Calibration Method= 0
Calibration Iterations= 20
Calibration Max Change=0.05
Calibration Tolerance=0.2
Calibration Maximum=1.5
Calibration Minimum=0.5
Calibration Optimization Method= 1
WQ AD Non Conservative
WQ ULTIMATE=-1
WQ Max Comp Step=1HOUR
WQ Output Interval=15MIN
WQ Output Selected Increments= 0
WQ Output face flow=0
WQ Output face velocity=0
WQ Output face area=0
WQ Output face dispersion=0
WQ Output cell volume=0
WQ Output cell surface area=0
WQ Output cell continuity=0
WQ Output cumulative cell continuity=0
WQ Output face conc=0
WQ Output face dconc_dx=0
WQ Output face courant=0
WQ Output face peclet=0
WQ Output face adv mass=0
WQ Output face disp mass=0
WQ Output cell mass=0
WQ Output cell source sink temp=0
WQ Output nsm pathways=0
WQ Output nsm derived pathways=0
WQ Create Restart=0
WQ Fixed Restart=0
WQ System Summary=0
WQ Write To DSS=0
Sorting and Armoring Iterations= 10
XS Update Threshold= 0.02
Bed Roughness Predictor= 0
Hydraulics Update Threshold= 0.02
Energy Slope Method= 1
Volume Change Method= 1
Sediment Retention Method= 0
Sediment TS Multiplier= 1
Warm Up Method= 0
XS Weighting Method= 0
Number of US Weighted Cross Sections= 1
Number of DS Weighted Cross Sections= 1
Upstream XS Weight=0
Main XS Weight=1
Downstream XS Weight=0
Number of DS XS's Weighted with US Boundary= 1
Upstream Boundary Weight= 1
Weight of XSs Associated with US Boundary= 0
Number of US XS's Weighted with DS Boundary= 1
Downstream Boundary Weight= 0.5
Weight of XSs Associated with DS Boundary= 0.5
Percentile Method= 0
Sediment Output Level= 3
Mass or Volume Output= 0
Output Increment Type= 1
Profile and TS Output Increment= 1
Transport Output Increment 1
XS Output Flag= 0
XS Output Increment= 10
Read HDF5 Sediment Hotstart= 0
Sediment Hotstart Type= 0
Write Gradation File= 0
Read Gradation Hotstart= 0
Write HDF5 File= 1
Write Binary Output= 1
Write DSS Sediment File= 0
DSS Sediment Output Type= 1
SV Curve= 0
Specific Gage Flag= 0
Subcell Erosion Methods= 0
Subcell Deposition Methods= 0
Advection Scheme= 1
Matrix Solver= 0
Implicit Weighting Factor= 1
Maximum Outer Loop Convergence Iterations= 5
Convergence Maximum Absolute= 0.001
Convergence RMSE= 0.0001
Grain Fractions Max Abs Error= 0.001
Max Subgrid Regions= 1
Max Subgrid Length Scale= 3.402823E+38
Initial Layer Thickness= 3.402823E+38
Min Layer Thickness= 3.402823E+38
Max Layer Thickness= 3.402823E+38
Number of Layers= 5

--- WARNERRN.f01 (steady flow) ---

Flow Title=Flow
Program Version=6.20
Number of Profiles= 1
Profile Names=P100yr
River Rch & RM=WARNERRN,Main            ,3651
    1960
River Rch & RM=WARNERRN,Main            ,0
    2510
Boundary for River Rch & Prof#=WARNERRN,Main            , 1
Up Type= 0
Dn Type= 1
Dn Known WS=3440.51
DSS Import GetInterval= 0
DSS Import GetPeak= 0
DSS Import FillOption= 0

--- WARNERRN.g01 (geometry) ---

Geom Title=Geometry
Program Version=6.20

River Reach=WARNERRN        ,Main
Reach XY= 30
2357981.74105624628777.7960699872358085.60826609628810.777728274
2358398.47700001629002.8649999952358480.55800003629032.016000018
2358528.88600004629033.5499999972358789.04100002628810.645999998
2358842.30100001628787.4970000092358884.82199998 628792.99500002
     2358951.458628838.8290000112358995.54600005628888.104000017
2359046.60500002628979.3100000172359111.29600002629044.751000002
2359152.16900003629058.362000018     2359276.942629064.736000016
2359346.93500003629130.4660000212359564.31700002629213.552000001
2359790.11900003629323.5820000172359803.83200003 629345.43900001
2359818.72600001629578.4099999962359881.35700001629832.338000014
      2359917.97629893.2370000032359960.38300002629921.084999993
     2360040.037629929.392000005     2360080.222629979.823000014
2360120.31000003630290.6979999992360094.10600001 630357.05400002
     2360095.528630392.8100000022360164.58800003630550.378000006
2360177.54100004630635.240999997 2360197.5588765630659.804543682

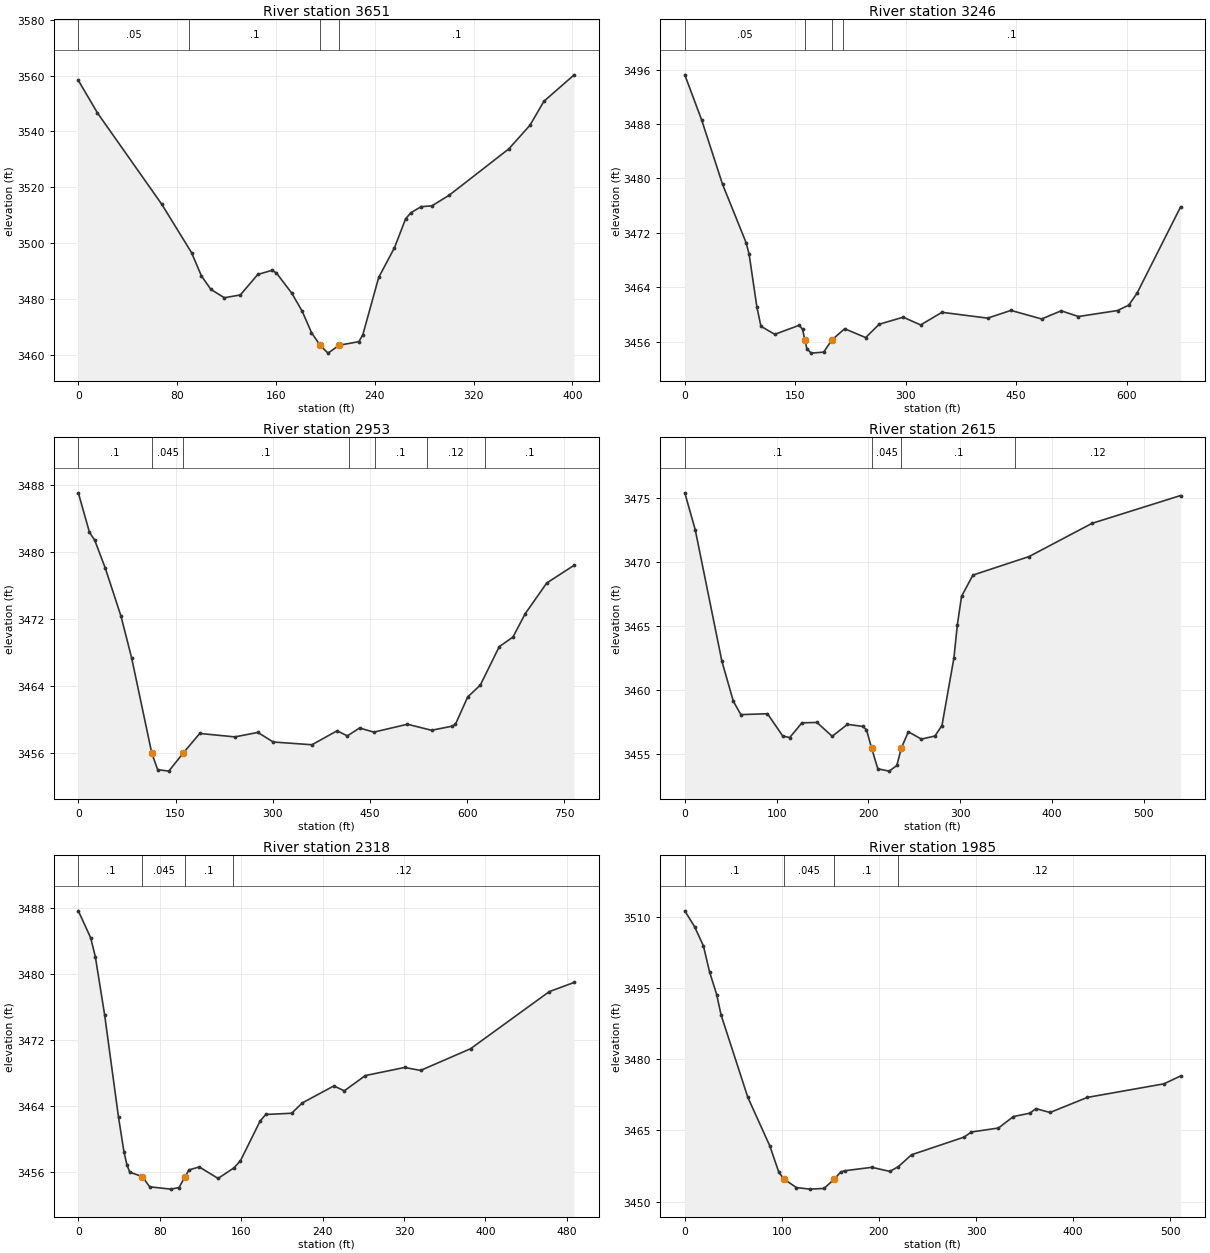
Type RM Length L Ch R = 1 ,3651    ,405.3,405.3,405.3
XS GIS Cut Line= 5
2357832.66137486628870.0653627072357935.54917839628864.317440722
 2357971.1862947628825.806363421 2358009.1225798628702.800832939
2357934.97438619628611.983665574
#Sta/Elev= 30
       0 3558.27    15.5  3546.6    67.6 3513.87    91.7 3496.55    99.7 3488.22
   107.3 3483.43   118.2 3480.42   131.2 3481.42   145.3 3488.76   156.8 3490.23
   160.4  3489.3   172.9 3482.01   181.3 3475.56   188.8 3467.94  195.85 3463.34
   202.2 3460.58   211.2 3463.41   227.2 3464.69   230.4 3467.22   243.2 3487.69
     256 3498.35     265 3508.68   269.2 3510.85   277.6 3513.04   286.3 3513.33
   300.3 3517.14   348.6 3533.75   365.7  3542.2     377 3550.79401.4831 3560.26
#Mann= 4 ,-1,0
       0     .05       0      90      .1       0  195.85    .045       0
   211.2      .1       0
Bank Sta=195.85,211.2
XS Rating Curve= 0 ,0
Exp/Cntr(USF)=0,0
Exp/Cntr=0.3,0.1

Type RM Length L Ch R = 1 ,3246    ,293.1,293.1,293.1
XS GIS Cut Line= 4
2358284.38987308629144.0982190962358294.31448071629040.379043632
2358381.92188789628903.0192817572358185.32283043 628547.54429597
#Sta/Elev= 30
       0 3495.26      23 3488.58    51.2 3479.16    83.3 3470.54    87.3 3468.88
    97.8 3461.14   103.4 3458.24   122.2 3457.06   155.4 3458.39     160 3457.77
   162.9 3456.26   165.8 3454.94   171.6 3454.29   188.6 3454.44  199.89 3456.25
   217.1 3457.88   245.6 3456.58   263.9 3458.54   296.6 3459.58   320.3 3458.44
   349.2  3460.3   411.2 3459.44   442.9 3460.58   484.6 3459.32   511.1 3460.52
   534.6 3459.68   587.6 3460.56   602.9 3461.36   614.1 3463.11   673.3 3475.83
#Mann= 4 ,-1,0
       0     .05       0   162.9    .045       0  199.89     .05       0
  214.19      .1       0
Bank Sta=162.9,199.89
XS Rating Curve= 0 ,0
Exp/Cntr(USF)=0,0
Exp/Cntr=0.3,0.1

Type RM Length L Ch R = 1 ,2953    ,338.3,338.3,338.3
XS GIS Cut Line= 3
2358639.08629595629106.0769614452358621.93137013629009.943342286
 2358231.4389366628468.506679831
#Sta/Elev= 30
       0 3487.06    17.2 3482.34    25.3  3481.4    41.5 3478.09    65.9 3472.31
    82.2 3467.36   113.4 3455.96   122.4    3454   139.6 3453.82   162.2 3456.01
   187.4 3458.32   241.6 3457.91   277.1 3458.44   300.8  3457.3   360.5 3456.97
   399.4 3458.64   415.2 3458.03     434 3458.97   456.2 3458.48   507.9 3459.42
   545.1  3458.7     577 3459.19   581.9  3459.4   600.9 3462.68   620.4  3464.1
   649.6 3468.69   670.7 3469.83   689.7 3472.63   722.9 3476.29   765.2 3478.41
#Mann= 7 ,-1,0
       0      .1       0   113.4    .045       0   162.2      .1       0
  417.65     .12       0  457.65      .1       0  537.65     .12       0
  627.65      .1       0
Bank Sta=113.4,162.2
XS Rating Curve= 0 ,0
Exp/Cntr(USF)=0,0
Exp/Cntr=0.3,0.1

Type RM Length L Ch R = 1 ,2615    ,297.5,297.5,297.5
XS GIS Cut Line= 2
 2358811.0902292629000.2052224862358951.97301406628478.683101155
#Sta/Elev= 30
       0 3475.38    11.4 3472.49    40.4 3462.24    52.9 3459.11    61.1 3458.07
    90.1 3458.14   106.7  3456.4   114.3 3456.28   127.6 3457.43     144 3457.46
   160.6 3456.38   177.2 3457.31   193.7 3457.15   197.9  3456.9   203.6 3455.44
   210.3 3453.84   222.7 3453.66     231  3454.1   235.9 3455.45   243.5 3456.73
   257.8 3456.16   272.5  3456.4   280.2 3457.22   293.2 3462.49   296.9 3465.06
   301.5  3467.3   313.9 3468.96   375.2 3470.41   443.7    3473   540.2 3475.17
#Mann= 4 ,-1,0
       0      .1       0   203.6    .045       0   235.9      .1       0
     360     .12       0
Bank Sta=203.6,235.9
XS Rating Curve= 0 ,0
Exp/Cntr(USF)=0,0
Exp/Cntr=0.3,0.1

Type RM Length L Ch R = 1 ,2318    ,332.5,332.5,332.5
XS GIS Cut Line= 3
2359013.78021579629075.7972294832359034.04988538629038.811041335
2359315.70257504628694.407627079
#Sta/Elev= 30
       0 3487.64    12.1 3484.37    16.7 3482.08    25.8 3475.06    39.5 3462.59
    44.8 3458.45    47.7 3456.87    50.5 3455.95   62.77 3455.43    70.1 3454.18
    90.8  3453.9    98.9 3454.09  104.94 3455.43   108.7 3456.23   118.8 3456.59
   137.3  3455.2   152.8 3456.47   159.3 3457.35   178.6 3462.16   184.1 3462.95
   209.6  3463.1     220 3464.35     251 3466.41   261.3 3465.82     282 3467.67
   320.6 3468.65   336.2 3468.29   385.3 3470.92   462.6 3477.84   487.1 3478.96
#Mann= 4 ,-1,0
       0      .1       0   62.77    .045       0  104.94      .1       0
  152.18     .12       0
Bank Sta=62.77,104.94
XS Rating Curve= 0 ,0
Exp/Cntr(USF)=0,0
Exp/Cntr=0.3,0.1

Type RM Length L Ch R = 1 ,1985    ,342.8,342.8,342.8
XS GIS Cut Line= 3
2359290.39714973629238.053866278  2359493.117506628868.162868228
2359506.30301732628780.273771028
#Sta/Elev= 30
       0 3511.31    10.1 3507.96    19.2 3503.91    25.5 3498.43    32.9 3493.62
    37.3  3489.4    64.9 3471.99    87.7 3461.67    96.8  3456.2  102.093454.741
     115 3452.95   128.7 3452.62   143.4 3452.77  154.033454.741   160.6 3456.24
   165.2 3456.51   192.6 3457.22   211.2 3456.36     220 3457.37   233.6 3459.87
   287.8  3463.6     295 3464.66   323.1 3465.51   338.5 3467.93   355.5 3468.64
   361.6  3469.6   376.2 3468.78   414.5 3471.96   493.6 3474.83   510.7 3476.49
#Mann= 4 ,-1,0
       0      .1       0  102.09    .045       0  154.03      .1       0
     220     .12       0
Bank Sta=102.09,154.03
XS Rating Curve= 0 ,0
Exp/Cntr(USF)=0,0
Exp/Cntr=0.3,0.1

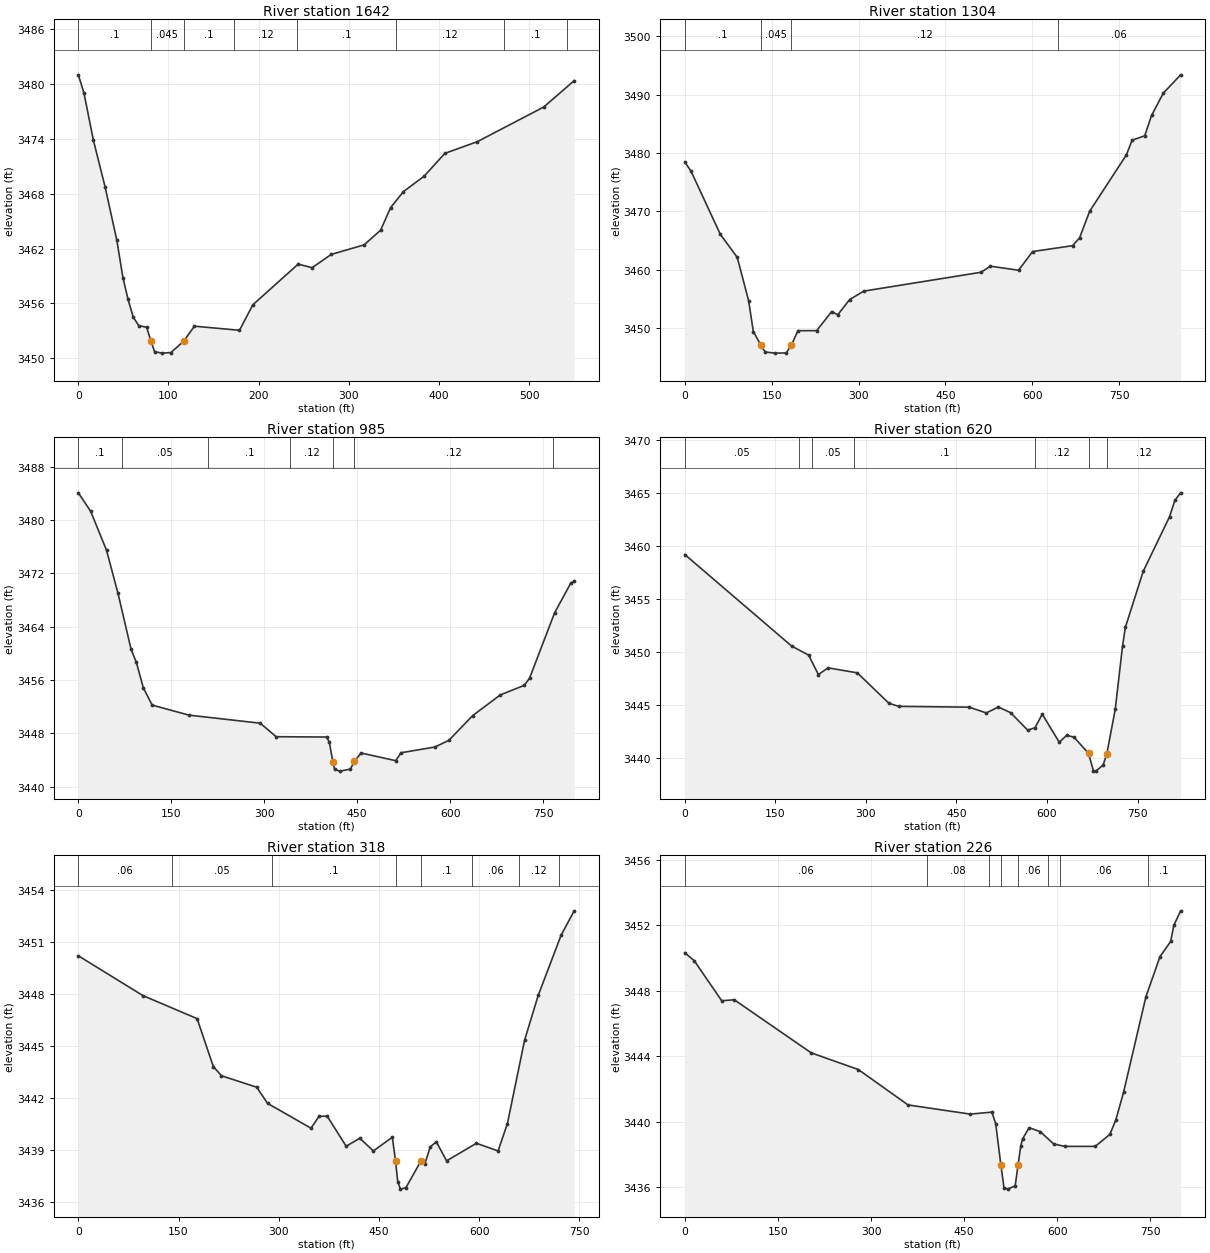
Type RM Length L Ch R = 1 ,1642    ,337.9,337.9,337.9
XS GIS Cut Line= 4
2359599.42086382629342.0973480112359640.07184123629308.097515416
2359780.52518529629054.8798261192359900.76924104628885.717144948
#Sta/Elev= 30
       0 3481.02     6.2 3479.05    16.6 3473.91    29.6 3468.79    42.7 3462.92
    49.5  3458.8    55.2 3456.43    60.9  3454.5      67 3453.57    75.8 3453.39
   80.613451.863    84.6 3450.72    92.9 3450.56   102.7 3450.62  116.873451.865
   128.8 3453.51   178.8 3453.06   193.6 3455.85   243.9  3460.3   259.4 3459.91
   280.5 3461.36   317.1 3462.41   335.4 3464.02   346.4 3466.48   360.7 3468.24
   383.7 3469.93   406.6 3472.42   442.8 3473.71   516.4  3477.5   550.1 3480.38
#Mann= 8 ,-1,0
       0      .1       0   80.61    .045       0  116.87      .1       0
     173     .12       0     243      .1       0  352.56     .12       0
  472.56      .1       0  542.56     .12       0
Bank Sta=80.61,116.87
XS Rating Curve= 0 ,0
Exp/Cntr(USF)=0,0
Exp/Cntr=0.3,0.1

Type RM Length L Ch R = 1 ,1304    ,319.9,319.9,319.9
XS GIS Cut Line= 4
2359662.76185284629492.8546293072359738.46401586629529.570166804
2360336.93436944629433.4303509692360476.22112836629343.873075511
#Sta/Elev= 30
       0 3478.46    10.5 3476.95    61.2 3466.11    90.6 3462.13   110.2 3454.71
   118.3 3449.45  131.243447.131   138.8 3445.94   155.8 3445.75     175 3445.78
  184.05 3447.13   195.3 3449.59   227.7  3449.6   253.5 3452.86   264.1 3452.32
   284.4  3454.9   308.7 3456.36   511.3 3459.59   527.5 3460.63   576.1 3459.94
   600.4 3463.14   669.3 3464.14   681.4 3465.47   698.9 3470.04   762.3 3479.69
   772.1 3482.19     794 3482.96   805.7 3486.43     826 3490.25   855.9 3493.39
#Mann= 4 ,-1,0
       0      .1       0  131.24    .045       0  184.05     .12       0
  644.14     .06       0
Bank Sta=131.24,184.05
XS Rating Curve= 0 ,0
Exp/Cntr(USF)=0,0
Exp/Cntr=0.3,0.1

Type RM Length L Ch R = 1 ,985     ,364.1,364.1,364.1
XS GIS Cut Line= 4
2359550.64781696629686.4394226932359736.06052047629885.287485393
2360103.79531604629743.4812570372360215.18584674629818.011232615
#Sta/Elev= 30
       0 3484.11    19.8 3481.35    45.5 3475.48    63.9 3469.05    85.1 3460.61
    93.6 3458.64   104.9 3454.82   119.1 3452.23   178.5 3450.72   293.4 3449.51
   319.2 3447.48   400.6 3447.43   404.9 3446.69  410.57 3443.75   413.5 3442.56
   422.1 3442.31   438.9 3442.61  445.26 3443.76   456.3 3445.03   512.1 3443.88
   520.7 3445.07   575.3 3445.93   597.8 3446.93   636.4 3450.66   680.9 3453.76
   719.4 3455.19   728.1 3456.28   768.4 3466.08   794.4 3470.53     800 3470.86
#Mann= 7 ,-1,0
       0      .1       0      70     .05       0     210      .1       0
  341.88     .12       0  410.57    .045       0  445.26     .12       0
  766.01      .1       0
Bank Sta=410.57,445.26
XS Rating Curve= 0 ,0
Exp/Cntr(USF)=0,0
Exp/Cntr=0.3,0.1

Type RM Length L Ch R = 1 ,620     ,302.2,302.2,302.2
XS GIS Cut Line= 3
2359416.61148755630156.2218557342360137.44425158630065.549640084
 2360214.7527286630010.457227152
#Sta/Elev= 30
       0 3459.18   176.9 3450.55   205.2 3449.69   221.3 3447.86   237.4 3448.49
   285.8 3448.02   338.2 3445.15   354.3 3444.86   471.2 3444.78   499.5 3444.24
   519.6  3444.8   539.8 3444.26     568 3442.62   580.1 3442.84   592.2 3444.12
   620.4 3441.47   632.5 3442.12   644.6 3441.96   668.8 3440.43   676.9 3438.79
   680.9 3438.75     693 3439.32  699.24 3440.41   713.1 3444.59   725.2 3450.56
   729.9 3452.32   759.3 3457.58     803 3462.74   811.9 3464.29   821.4    3465
#Mann= 7 ,-1,0
       0     .05       0     190      .1       0     210     .05       0
     280      .1       0     580     .12       0   668.8    .045       0
  699.24     .12       0
Bank Sta=668.8,699.24
XS Rating Curve= 0 ,0
Exp/Cntr(USF)=0,0
Exp/Cntr=0.3,0.1

Type RM Length L Ch R = 1 ,318     ,92.6,92.6,92.6
XS GIS Cut Line= 3
 2359609.0484176630449.8958219032360238.72844834630340.277280837
2360300.22884818630257.488281052
#Sta/Elev= 30
       0 3450.19    96.6  3447.9   177.8 3446.57   202.1 3443.81   214.3 3443.28
   267.1 3442.62   283.3 3441.69   348.3 3440.26   360.5 3440.95   372.6 3440.95
     401 3439.22   421.4 3439.68   441.7 3438.95   470.1 3439.74   474.9 3438.37
   478.2 3437.17   482.3 3436.75   490.4 3436.83  512.62 3438.35   518.8 3438.21
   526.9 3439.18   535.9 3439.48   551.3 3438.38     596 3439.39   628.4 3438.95
   642.4 3440.53   668.1 3445.33   688.5 3447.91   722.7 3451.37   742.3 3452.78
#Mann= 8 ,-1,0
       0     .06       0     140     .05       0     290      .1       0
   474.9    .045       0  512.62      .1       0     590     .06       0
  659.15     .12       0  719.15      .1       0
Bank Sta=474.9,512.62
XS Rating Curve= 0 ,0
Exp/Cntr(USF)=0,0
Exp/Cntr=0.3,0.1

Type RM Length L Ch R = 1 ,226     ,34.4,34.4,34.4
XS GIS Cut Line= 5
2359600.54342069630477.8650668622360050.08607807630473.414149462
2360094.59525207630465.9959537962360238.50824799630393.297636266
2360326.04295686630280.541062138
#Sta/Elev= 30
       0 3450.32    15.1 3449.84    59.5 3447.39    79.7 3447.45   203.6 3444.21
   279.6 3443.19   359.6 3441.03   459.8 3440.47   494.7 3440.59   500.9 3439.87
  509.12 3437.37   514.2 3435.98   520.3 3435.89   532.2 3436.09   536.8 3437.36
   541.1 3438.51   544.1 3438.96   554.7 3439.64   572.6  3439.4   594.1 3438.65
   611.8  3438.5   661.1  3438.5   684.7 3439.23   694.3 3440.11   706.7 3441.79
   742.7 3447.62   765.5 3450.09   782.7 3451.01   787.7 3451.99   798.7 3452.88
#Mann= 8 ,-1,0
       0     .06       0     390     .08       0  489.56     .06       0
  509.12    .045       0   536.8     .06       0  584.69      .1       0
  604.69     .06       0  745.92      .1       0
Bank Sta=509.12,536.8
XS Rating Curve= 0 ,0
Exp/Cntr(USF)=0,0
Exp/Cntr=0.3,0.1

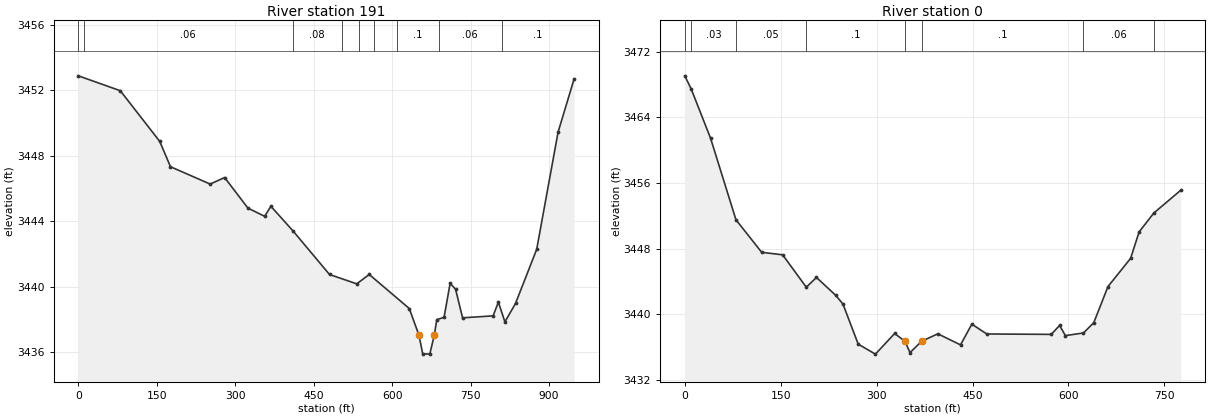
Type RM Length L Ch R = 1 ,191     ,107,107,107
XS GIS Cut Line= 5
2359471.96275746630507.3660409122360070.69109511630501.523139153
2360115.20026911630494.1049434872360259.11326504630421.406625957
 2360346.6479739630308.650051829
#Sta/Elev= 30
       0 3452.89    80.2 3451.98   155.6 3448.88   176.2 3447.33     252 3446.27
   279.7 3446.67   324.2  3444.8   356.2  3444.3   368.2 3444.91     410 3443.42
   480.2 3440.74   532.2 3440.17   556.2 3440.74   632.7 3438.66651.23213437.022
   658.4 3435.89   671.9 3435.87680.61213437.048   685.3 3437.98   699.2 3438.12
   710.8  3440.2   721.2 3439.84   734.6 3438.09   792.9 3438.21   803.1 3439.05
   815.5 3437.84   835.8 3438.97   876.3 3442.28   917.2 3449.45   947.9 3452.71
#Mann= 9 ,-1,0
       0     .05       0      10     .06       0     410     .08       0
  503.62     .06       0   536.1    .045       0  565.48     .06       0
  608.75      .1       0  688.75     .06       0  809.98      .1       0
Bank Sta=651.2321,680.6121
XS Rating Curve= 0 ,0
Exp/Cntr(USF)=0,0
Exp/Cntr=0.3,0.1

Type RM Length L Ch R = 1 ,0       ,556,556,556
XS GIS Cut Line= 3
2360186.78904024630991.507112601 2360126.8235474630807.554410706
2360378.08603325630282.724748537
#Sta/Elev= 30
       0 3469.08      103467.476    40.3 3461.46      803451.513   120.2 3447.54
     153 3447.23     1903443.279   205.9 3444.47     236 3442.29   247.3 3441.23
   271.2 3436.33   298.1 3435.11   328.2 3437.63  344.33 3436.67   352.2 3435.29
   370.2 3436.67   395.7 3437.59   431.2 3436.24   448.9 3438.77   472.2 3437.57
   573.1 3437.52   586.1 3438.61   595.2 3437.37  623.483437.695   639.6 3438.95
   661.8 3443.36   697.2  3446.8   710.5 3450.03  733.483452.334   775.4  3455.1
#Mann= 8 ,-1,0
       0     .05       0      10     .03       0      80     .05       0
     190      .1       0  344.33    .045       0   370.2      .1       0
  623.48     .06       0  733.48      .1       0
Bank Sta=344.33,370.2
XS Rating Curve= 0 ,0
Exp/Cntr=0.3,0.1
LCMann Table=0

Chan Stop Cuts=-1
Use User Specified Reach Order=0
Composite Channel Slope=5