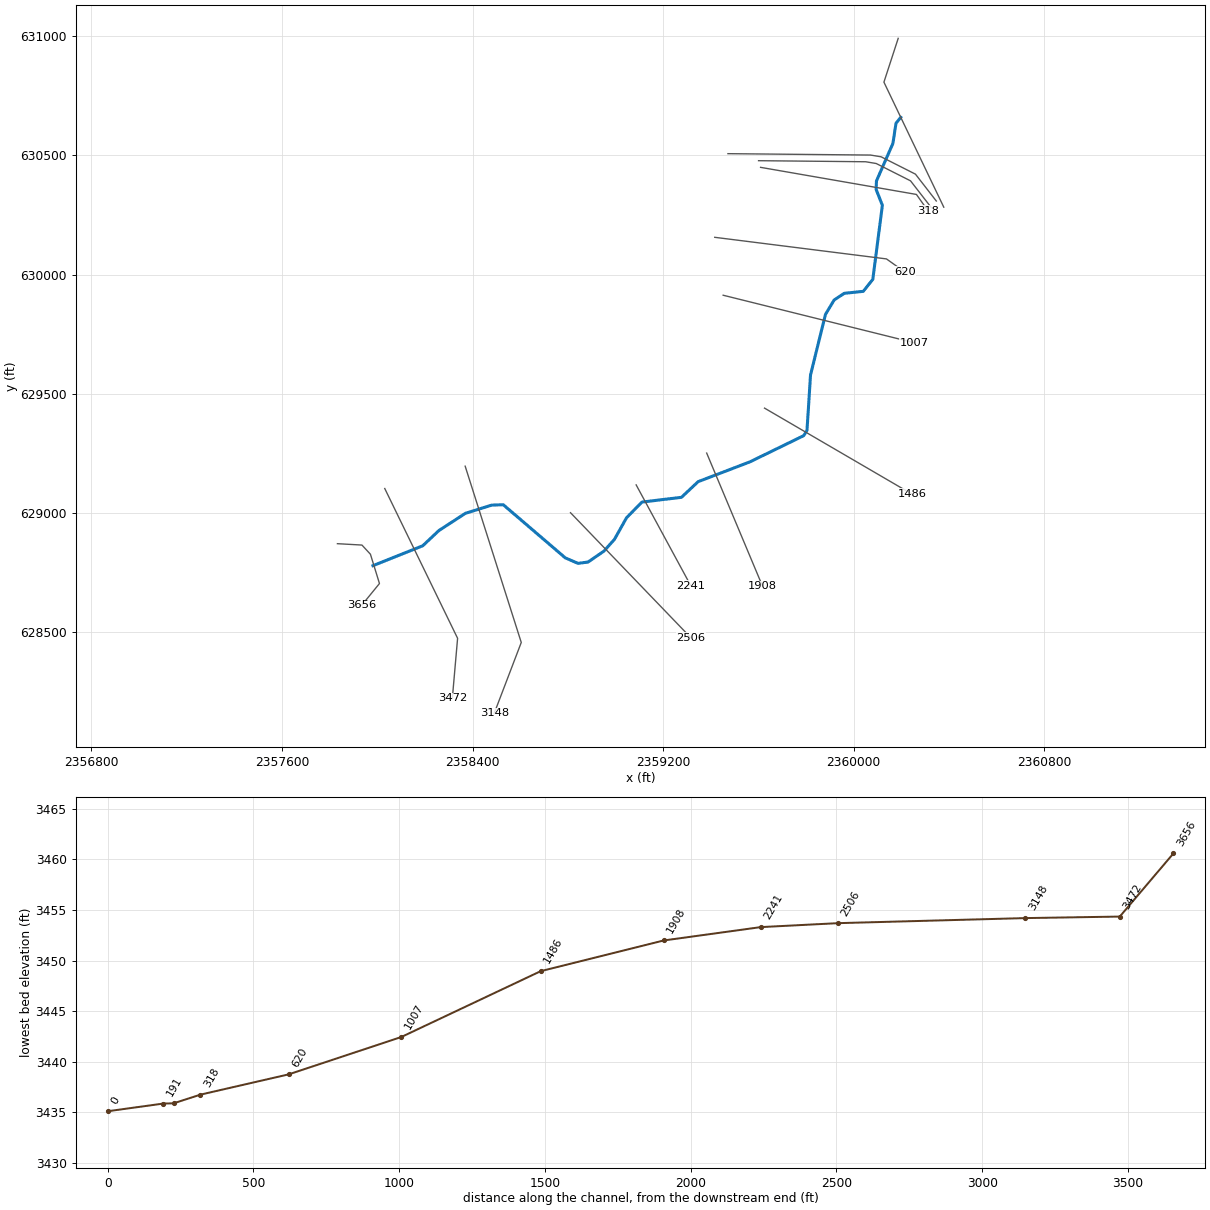
--- WARNERRN.prj (project) ---

Proj Title=WARNERRN
Current Plan=p01
Default Exp/Contr=0,0
English Units
Geom File=g01
Flow File=f01
Plan File=p01
BEGIN DESCRIPTION:
----------MODEL BY WOOD PLC 2022----------
AFH study
Randolph County, WV
HEC-RAS Version: RAS 6.2
Vertical Datum: NAVD88
Projection: NAD 1983 StatePlane West Virginia S FIPS 4702 (US Feet)
Terrain: 1-meter LIDAR (FEMA Region III 3DEP collected 2016-2018)
Land Use: 2019 NLCD
Hydrologic Method:
WV SIR2010-5033 regression equations
Additional Model Notes:
US extent ends but FACC grid and effective floodplain shows connection to GNDYCK_2 through karst area
END DESCRIPTION:
DSS Export Rating Curves= 0
DSS Export Rating Curve Sorted= 0
DSS Export Volume Flow Curves= 0
DXF OffsetX= 0
DXF OffsetY= 0
DXF ScaleX= 0
DXF ScaleY= 0

--- WARNERRN.p01 (plan) ---

Plan Title=Floodplain
Program Version=6.20
Short Identifier=Floodplain
Geom File=g01
Flow File=f01
Subcritical Flow
K Sum by GR= 0
Std Step Tol= 0.01
Critical Tol= 0.01
Num of Std Step Trials= 20
Max Error Tol= 0.3
Flow Tol Ratio= 0.001
Split Flow NTrial= 30
Split Flow Tol= 0.02
Split Flow Ratio= 0.02
Log Output Level= 0
Friction Slope Method= 1
Unsteady Friction Slope Method= 2
Unsteady Bridges Friction Slope Method= 1
Parabolic Critical Depth
Global Vel Dist= 0 , 0 , 0
Global Log Level= 0
CheckData=True
Encroach Param=-1 ,0,0, 0
Mapping Interval=1HOUR
Computation Time Step Use Courant=        0
Computation Time Step Use Time Series=    0
Computation Time Step Count To Double=0
Computation Time Step Max Doubling=0
Computation Time Step Max Halving=0
Computation Time Step Residence Courant=0
Run HTab= 0
Run UNet= 0
Run Sediment= 0
Run PostProcess= 0
Run WQNet= 0
Run RASMapper=-1
UNET Theta= 0
UNET Theta Warmup= 0
UNET ZTol= 0
UNET ZSATol= 0
UNET MxIter= 0
UNET Max Iter WO Improvement= 0
UNET MaxInSteps= 0
UNET DtIC= 0
UNET DtMin= 0
UNET MaxCRTS= 0
UNET WFStab= 0
UNET SFStab= 0
UNET WFX= 1
UNET SFX= 1
UNET Gravity=32.174
UNET 1D Methodology=Finite Difference
UNET DSS MLevel= 1
UNET Pardiso=0
UNET DZMax Abort= 0
UNET Use Existing IB Tables= 0
UNET Froude Reduction=False
UNET Froude Limit= 0
UNET Froude Power= 0
UNET D1 Cores= 0
UNET WindReference=Eulerian
UNET WindDragFormulation=Hsu (1988)
UNET D2 Coriolis=0
UNET D2 Cores= 0
UNET D2 Theta= 1
UNET D2 Theta Warmup= 1
UNET D2 Z Tol= 0.01
UNET D2 Volume Tol= 0.01
UNET D2 Max Iterations= 20
UNET D2 Equation= 0
UNET D2 RampUpFraction=0.1
UNET D2 TimeSlices= 1
UNET D2 Turbulence Formulation=Non-Conservative (original)
UNET D2 Eddy Viscosity=0.3
UNET D2 Transverse Eddy Viscosity=0.1
UNET D2 Smagorinsky Mixing=0
UNET D2 BCVolumeCheck=0
UNET D2 Cores=0
UNET D2 SolverType=PARDISO (Direct)
UNET D2 Minimum Iterations= 2147483647
UNET D2 Maximum Iterations= 2147483647
UNET D2 Restart Number= 10
UNET D2 Relaxation Coeff=1.3
UNET D2 SOR Precondition Iterations= 10
UNET D2 ILUT Maximum Fill= 8
UNET D2 ILUT Tolerance=1E-08
UNET D1D2 MaxIter= 0
UNET D1D2 ZTol=0.01
UNET D1D2 QTol=0.1
UNET D1D2 MinQTol=1
Write IC File= 0
Write IC File at Fixed DateTime=0
Write IC File at Sim End=0
Echo Input=False
Echo Parameters=False
Echo Output=False
Write Detailed= 0
HDF Write Warmup=0
HDF Write Time Slices=0
HDF Flush=0
HDF Compression= 1
HDF Chunk Size= 1
HDF Spatial Parts= 1
HDF Use Max Rows=0
HDF Fixed Rows= 1
Calibration Method= 0
Calibration Iterations= 20
Calibration Max Change=0.05
Calibration Tolerance=0.2
Calibration Maximum=1.5
Calibration Minimum=0.5
Calibration Optimization Method= 1
WQ AD Non Conservative
WQ ULTIMATE=-1
WQ Max Comp Step=1HOUR
WQ Output Interval=15MIN
WQ Output Selected Increments= 0
WQ Output face flow=0
WQ Output face velocity=0
WQ Output face area=0
WQ Output face dispersion=0
WQ Output cell volume=0
WQ Output cell surface area=0
WQ Output cell continuity=0
WQ Output cumulative cell continuity=0
WQ Output face conc=0
WQ Output face dconc_dx=0
WQ Output face courant=0
WQ Output face peclet=0
WQ Output face adv mass=0
WQ Output face disp mass=0
WQ Output cell mass=0
WQ Output cell source sink temp=0
WQ Output nsm pathways=0
WQ Output nsm derived pathways=0
WQ Create Restart=0
WQ Fixed Restart=0
WQ System Summary=0
WQ Write To DSS=0
Sorting and Armoring Iterations= 10
XS Update Threshold= 0.02
Bed Roughness Predictor= 0
Hydraulics Update Threshold= 0.02
Energy Slope Method= 1
Volume Change Method= 1
Sediment Retention Method= 0
Sediment TS Multiplier= 1
Warm Up Method= 0
XS Weighting Method= 0
Number of US Weighted Cross Sections= 1
Number of DS Weighted Cross Sections= 1
Upstream XS Weight=0
Main XS Weight=1
Downstream XS Weight=0
Number of DS XS's Weighted with US Boundary= 1
Upstream Boundary Weight= 1
Weight of XSs Associated with US Boundary= 0
Number of US XS's Weighted with DS Boundary= 1
Downstream Boundary Weight= 0.5
Weight of XSs Associated with DS Boundary= 0.5
Percentile Method= 0
Sediment Output Level= 3
Mass or Volume Output= 0
Output Increment Type= 1
Profile and TS Output Increment= 1
Transport Output Increment 1
XS Output Flag= 0
XS Output Increment= 10
Read HDF5 Sediment Hotstart= 0
Sediment Hotstart Type= 0
Write Gradation File= 0
Read Gradation Hotstart= 0
Write HDF5 File= 1
Write Binary Output= 1
Write DSS Sediment File= 0
DSS Sediment Output Type= 1
SV Curve= 0
Specific Gage Flag= 0
Subcell Erosion Methods= 0
Subcell Deposition Methods= 0
Advection Scheme= 1
Matrix Solver= 0
Implicit Weighting Factor= 1
Maximum Outer Loop Convergence Iterations= 5
Convergence Maximum Absolute= 0.001
Convergence RMSE= 0.0001
Grain Fractions Max Abs Error= 0.001
Max Subgrid Regions= 1
Max Subgrid Length Scale= 3.402823E+38
Initial Layer Thickness= 3.402823E+38
Min Layer Thickness= 3.402823E+38
Max Layer Thickness= 3.402823E+38
Number of Layers= 5

--- WARNERRN.f01 (steady flow) ---

Flow Title=Flow
Program Version=6.20
Number of Profiles= 1
Profile Names=P100yr
River Rch & RM=WARNERRN,Main,3656
    1960
Boundary for River Rch & Prof#=WARNERRN,Main            , 1
Up Type= 0
Dn Type= 1
Dn Known WS=3440.5
DSS Import GetInterval= 0
DSS Import GetPeak= 0
DSS Import FillOption= 0

--- WARNERRN.g01 (geometry) ---

Geom Title=Geometry
Program Version=6.20

River Reach=WARNERRN        ,Main
Reach XY= 30
2357981.74105623 628777.796069982358190.70640799628861.239719802
2358258.86200002628925.3869999952358369.86999672 628997.47869873
2358480.55800003629032.0160000182358528.88600004629033.549999997
2358789.04100002628810.6459999982358842.30100001628787.497000009
2358884.82199998 628792.99500002     2358951.458628838.829000011
2358995.54600005628888.1040000172359046.60500002628979.310000017
2359111.29600002629044.751000002     2359276.942629064.736000016
2359346.93500003629130.4660000212359564.31700002629213.552000001
2359790.11900003629323.5820000172359803.83200003 629345.43900001
2359818.72600001629578.4099999962359881.35700001629832.338000014
      2359917.97629893.2370000032359960.38300002629921.084999993
     2360040.037629929.392000005     2360080.222629979.823000014
2360120.31000003630290.6979999992360094.10600001 630357.05400002
     2360095.528630392.8100000022360164.58800003630550.378000006
2360177.54100004630635.2409999972360197.55878846630659.804727574

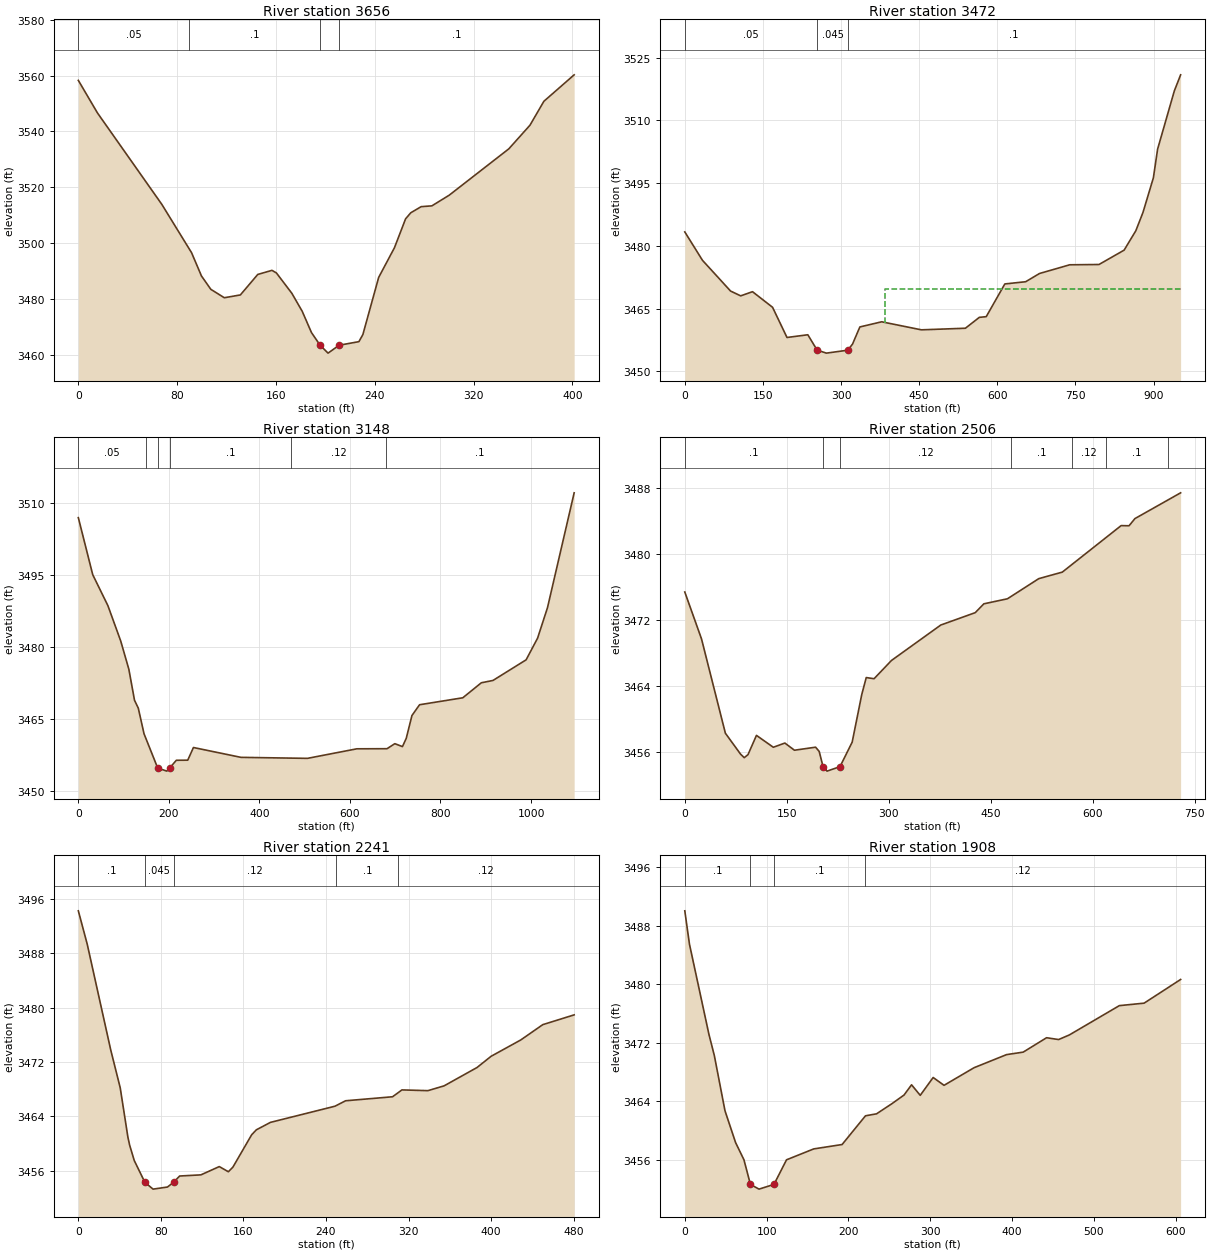
Type RM Length L Ch R = 1 ,3656    ,181.6,184.1,188.4
XS GIS Cut Line= 5
2357832.66137486628870.0653627072357935.54917839628864.317440722
 2357971.1862947628825.806363421 2358009.1225798628702.800832939
2357934.97438619628611.983665574
#Sta/Elev= 30
       0 3558.27    15.5  3546.6    67.6 3513.87    91.7 3496.55    99.7 3488.22
   107.3 3483.43   118.2 3480.42   131.2 3481.42   145.3 3488.76   156.8 3490.23
   160.4  3489.3   172.9 3482.01   181.3 3475.56   188.8 3467.94   195.83463.403
   202.2 3460.58   211.2 3463.41   227.2 3464.69   230.4 3467.22   243.2 3487.69
     256 3498.35     265 3508.68   269.2 3510.85   277.6 3513.04   286.3 3513.33
   300.3 3517.14   348.6 3533.75   365.7  3542.2     377 3550.79   401.5 3560.26
#Mann= 4, -1 ,  0
       0    0.05       0      90     0.1       0   195.8   0.045       0
   211.2     0.1       0
Bank Sta=195.8,211.2
XS Rating Curve= 0 ,0
Exp/Cntr(USF)=0,0
Exp/Cntr=0.3,0.1

Type RM Length L Ch R = 1 ,3472    ,322.6,323.7,323.4
XS GIS Cut Line= 3
2358031.33228272629101.6281955362358337.11160727 628472.90307746
2358315.06244503628221.146739239
#Sta/Elev= 30
       0 3483.32    33.9 3476.54    87.8 3469.19   107.3 3468.03     130 3469.03
   168.5  3465.3   196.2 3458.08   236.2 3458.73     254 3455.07   271.8 3454.34
   312.9 3455.04     322  3456.5   336.1  3460.6     378 3461.83   454.2 3459.91
   538.7 3460.29   565.4 3462.89   578.7 3463.06   614.4 3470.88   654.4 3471.41
     681 3473.38     739 3475.46   795.2 3475.53   843.4 3478.96   865.9  3483.6
   879.6 3487.97   899.6 3496.25   907.7 3503.11   939.8 3517.03   951.9 3520.88
#Mann= 3, -1 ,  0
       0    0.05       0     254   0.045       0   312.9     0.1       0
#XS Ineff= 2 , 0
                          384.84         3469.65
Permanent Ineff=
       F       F
Bank Sta=254,312.9
XS Rating Curve= 0 ,0
Exp/Cntr(USF)=0,0
Exp/Cntr=0.3,0.1

Type RM Length L Ch R = 1 ,3148    ,639.3,642.6,648.9
XS GIS Cut Line= 3
2358368.89034737629195.4807460232358604.39472306628455.344332627
2358490.72306864628157.716896285
#Sta/Elev= 30
       0    3507    31.8 3495.12    65.4 3488.65    93.6 3481.31   111.6 3475.42
   124.1 3468.96   132.5  3467.3   145.1 3461.98  175.31 3454.84   195.5 3454.19
  201.63 3454.83   216.5 3456.45   241.7 3456.47   254.3 3459.11   359.2 3457.06
   506.1 3456.85   615.3 3458.84   681.9 3458.86   699.2 3459.91     716  3459.3
   724.4 3461.02     737 3465.78   753.8 3468.02   849.3 3469.47   890.3  3472.6
     916 3473.08   989.2 3477.38  1014.5 3481.89  1036.4 3488.24  1095.3 3512.17
#Mann= 6, -1 ,  0
       0    0.05       0     150     0.1       0  175.31   0.045       0
  201.63     0.1       0     470    0.12       0     680     0.1       0
Bank Sta=175.31,201.63
XS Rating Curve= 0 ,0
Exp/Cntr(USF)=0,0
Exp/Cntr=0.3,0.1

Type RM Length L Ch R = 1 ,2506    ,268.2,265,260
XS GIS Cut Line= 2
 2358811.0902292629000.2052224862359316.80471226628474.781157859
#Sta/Elev= 30
       0 3475.38    24.6  3469.7    59.7 3458.28    82.1 3455.74    87.5 3455.32
      93 3455.69   105.4 3458.02   130.2 3456.58   147.2 3457.09   161.3 3456.22
   192.4 3456.59   197.7 3456.07   203.4 3454.22   209.2 3453.69   228.33454.233
   246.2  3457.2   260.3 3462.97   266.9 3465.02   278.4 3464.88     304 3467.09
   376.5 3471.38   427.2 3472.88   439.9 3473.95   474.6 3474.56   520.7    3477
   555.3 3477.79   641.8 3483.42   653.4  3483.4   662.1 3484.27   729.3 3487.39
#Mann= 7, -1 ,  0
       0     0.1       0   203.4   0.045       0   228.3    0.12       0
     480     0.1       0     570    0.12       0     620     0.1       0
     710    0.12       0
Bank Sta=203.4,228.3
XS Rating Curve= 0 ,0
Exp/Cntr(USF)=0,0
Exp/Cntr=0.3,0.1

Type RM Length L Ch R = 1 ,2241    ,333.3,333.1,330.7
XS GIS Cut Line= 2
2359086.72611988 629116.849907262359315.70257504628694.407627079
#Sta/Elev= 30
       0 3494.28     8.7 3489.32    31.5 3473.73    40.6 3468.22      48 3460.99
    49.7 3459.79    54.2 3457.51   64.48 3454.31    72.4  3453.3    86.4 3453.61
    92.3 3454.31    98.2 3455.23   118.8  3455.4   136.6 3456.62   145.4 3455.86
   149.8 3456.54     168 3461.31   172.5 3462.03   186.2 3463.13   248.7 3465.51
     259 3466.31   304.5  3466.9   313.6 3467.91   338.8  3467.8   354.5 3468.51
   386.4 3471.21     400 3472.86   428.7 3475.26   450.1 3477.52   480.5 3478.96
#Mann= 5, -1 ,  0
       0     0.1       0   64.48   0.045       0    92.3    0.12       0
     250     0.1       0     310    0.12       0
Bank Sta=64.48,92.3
XS Rating Curve= 0 ,0
Exp/Cntr(USF)=0,0
Exp/Cntr=0.3,0.1

Type RM Length L Ch R = 1 ,1908    ,413.7,422.1,438
XS GIS Cut Line= 2
2359382.76980435629250.4522911022359617.16503025628691.691854317
#Sta/Elev= 30
       0 3490.05     5.7 3485.49    29.5 3473.15    36.1 3470.25    49.1 3462.71
    62.1 3458.34    72.3 3455.99    80.23452.621    90.7 3451.98     109 3452.63
   124.3 3455.99   157.5 3457.48   192.2 3458.08   220.8 3462.01   234.3 3462.28
     253 3463.66   267.9 3464.85   277.1 3466.25   287.7 3464.81   303.5 3467.25
   316.8 3466.18   353.5 3468.59   393.2 3470.38   413.5 3470.72   442.1 3472.69
   456.8 3472.44   469.9 3473.07     531 3477.08   561.3 3477.42   605.9 3480.66
#Mann= 4, -1 ,  0
       0     0.1       0    80.2   0.045       0     109     0.1       0
     220    0.12       0
Bank Sta=80.2,109
XS Rating Curve= 0 ,0
Exp/Cntr(USF)=0,0
Exp/Cntr=0.3,0.1

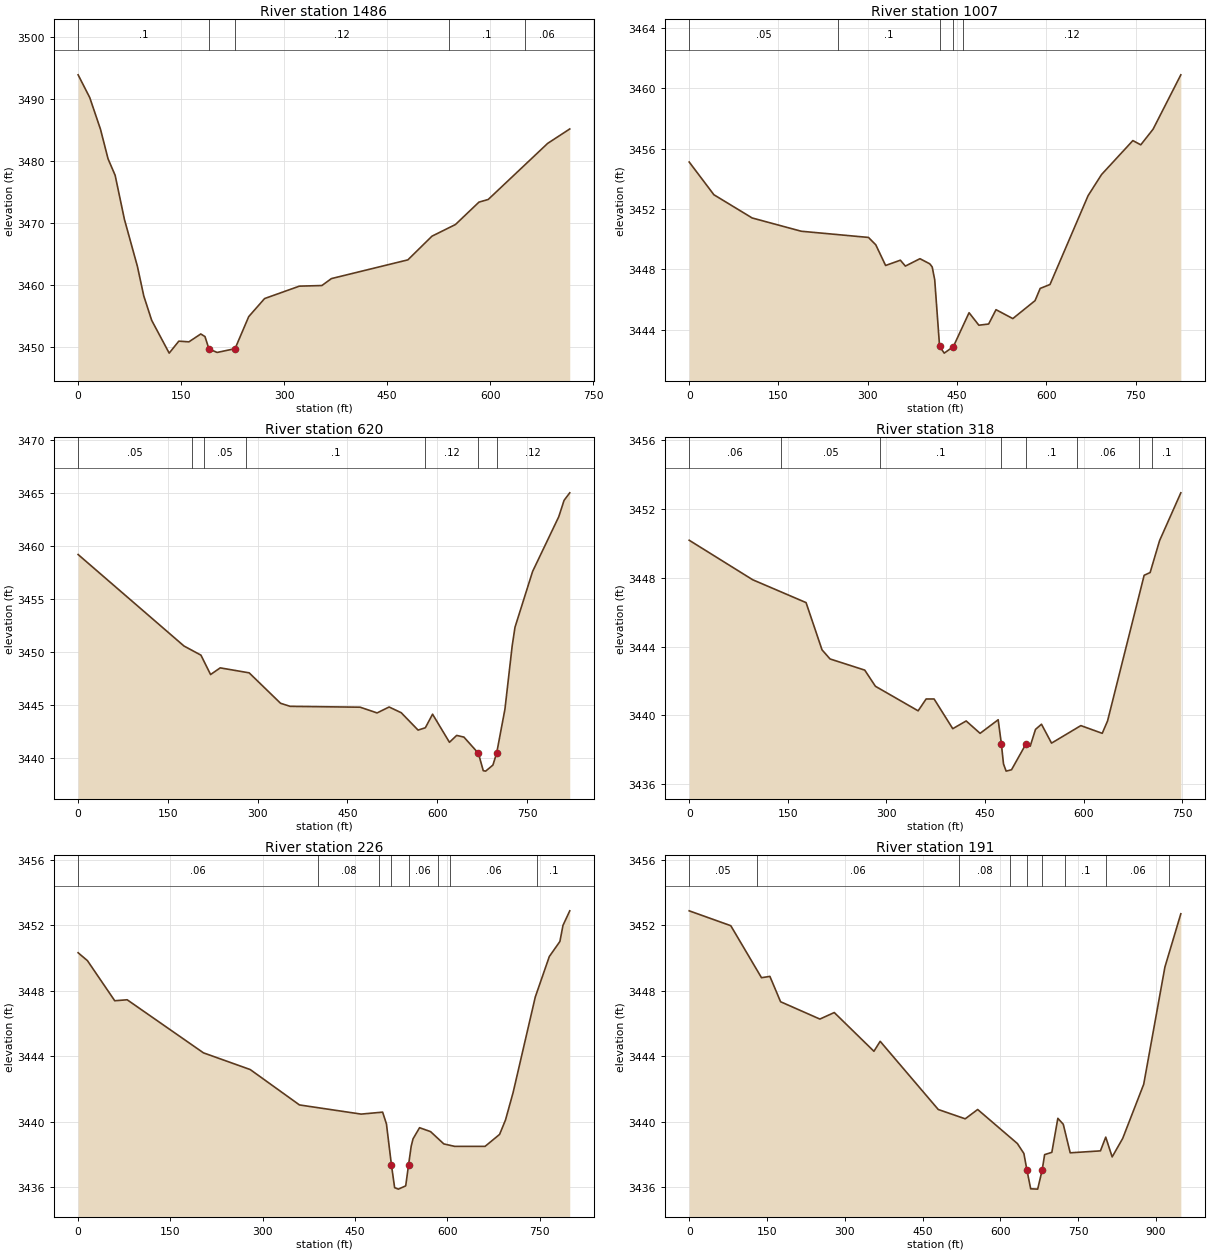
Type RM Length L Ch R = 1 ,1486    ,475.6,478.7,488
XS GIS Cut Line= 2
2359625.61046358629439.1529236062360243.97320049629078.553376309
#Sta/Elev= 30
       0 3493.83    16.9 3490.17    32.6 3485.04    43.6 3480.28    53.9 3477.63
    67.4 3470.53    86.3 3462.95    95.6 3458.17   107.1 3454.24   132.6 3448.95
   146.6 3450.88   161.3 3450.77   178.6 3452.04   184.7 3451.62   190.5 3449.63
   190.5 3449.62   202.4 3449.06   228.5 3449.67   248.4 3454.84   271.5 3457.75
   322.1 3459.75   354.9 3459.85   368.8 3460.97   480.1 3463.99   515.2 3467.81
   549.4 3469.69   583.6  3473.3   597.1 3473.73   683.6 3482.77   715.8  3485.1
#Mann= 5, -1 ,  0
       0     0.1       0   190.5   0.045       0   228.5    0.12       0
     540     0.1       0     650    0.06       0
Bank Sta=190.5,228.5
XS Rating Curve= 0 ,0
Exp/Cntr(USF)=0,0
Exp/Cntr=0.3,0.1

Type RM Length L Ch R = 1 ,1007    ,386.3,386.5,394.9
XS GIS Cut Line= 2
2359451.90336141629913.0723555422360253.43856442629713.725836929
#Sta/Elev= 30
       0 3455.11    41.5 3452.94   105.8  3451.4   188.3 3450.52   301.2 3450.11
   313.5 3449.62     330 3448.25   354.8  3448.6   363.2 3448.21   387.7  3448.7
   404.2 3448.36   408.3 3448.15   412.5  3447.3   420.7 3442.88   428.5 3442.44
  443.79 3442.87   470.2 3445.12   486.7 3444.29   503.1 3444.37   515.5 3445.32
   543.7 3444.73   581.1 3445.92   589.7 3446.73   606.2 3446.99   670.2 3452.88
   692.8 3454.28   745.4 3456.53   758.7 3456.25   779.3 3457.28     826 3460.89
#Mann= 5, -1 ,  0
       0    0.05       0     250     0.1       0   420.7   0.045       0
  443.79     0.1       0     460    0.12       0
Bank Sta=420.7,443.79
XS Rating Curve= 0 ,0
Exp/Cntr(USF)=0,0
Exp/Cntr=0.3,0.1

Type RM Length L Ch R = 1 ,620     ,302.9,302.3,299.9
XS GIS Cut Line= 3
2359416.61148755630156.2218557342360137.44425158630065.549640084
 2360214.7527286630010.457227152
#Sta/Elev= 30
       0 3459.18   176.9 3450.55   205.2 3449.69   221.3 3447.86   237.4 3448.49
   285.8 3448.02   338.2 3445.15   354.3 3444.86   471.2 3444.78   499.5 3444.24
   519.6  3444.8   539.8 3444.26     568 3442.62   580.1 3442.84   592.2 3444.12
   620.4 3441.47   632.5 3442.12   644.6 3441.96   668.8 3440.43   676.9 3438.79
   680.9 3438.75     693 3439.32   699.33440.452   713.1 3444.59   725.2 3450.56
   729.9 3452.32   759.3 3457.58     803 3462.74   811.9 3464.29   821.4    3465
#Mann= 7, -1 ,  0
       0    0.05       0     190     0.1       0     210    0.05       0
     280     0.1       0     580    0.12       0   668.8   0.045       0
   699.3    0.12       0
Bank Sta=668.8,699.3
XS Rating Curve= 0 ,0
Exp/Cntr(USF)=0,0
Exp/Cntr=0.3,0.1

Type RM Length L Ch R = 1 ,318     ,96.9,92.5,87.7
XS GIS Cut Line= 3
 2359609.0484176630449.8958219032360263.21787137630336.195710331
2360311.79329795630267.692207316
#Sta/Elev= 30
       0 3450.19    96.6 3447.89   177.8 3446.56   202.1 3443.81   214.3 3443.28
   267.1 3442.63   283.3 3441.69   348.3 3440.26   360.5 3440.95   372.6 3440.95
     401 3439.22   421.4 3439.67   442.6 3438.95   470.1 3439.74   474.9 3438.35
   478.2 3437.17   482.2 3436.75   490.4 3436.83   512.63438.346   518.8  3438.2
   526.9 3439.18     536 3439.48   551.3 3438.38   595.9  3439.4   628.4 3438.95
   636.5 3439.67   692.2 3448.15   701.3 3448.31   715.6 3450.16     748 3452.95
#Mann= 8, -1 ,  0
       0    0.06       0     140    0.05       0     290     0.1       0
   474.9   0.045       0   512.6     0.1       0     590    0.06       0
  683.98    0.12       0  703.98     0.1       0
Bank Sta=474.9,512.6
XS Rating Curve= 0 ,0
Exp/Cntr(USF)=0,0
Exp/Cntr=0.3,0.1

Type RM Length L Ch R = 1 ,226     ,34.4,34.4,34.4
XS GIS Cut Line= 5
2359600.54342069630477.8650668622360050.08607807630473.414149462
2360094.59525207630465.9959537962360238.50824799630393.297636266
2360326.04295686630280.541062138
#Sta/Elev= 30
       0 3450.32    15.1 3449.84    59.5 3447.39    79.7 3447.45   203.6 3444.21
   279.6 3443.19   359.6 3441.03   459.8 3440.47   494.7 3440.59   500.9 3439.87
   509.13437.337   514.2 3435.98   520.3 3435.89   532.2 3436.09   536.8 3437.36
   541.1 3438.51   544.1 3438.96   554.7 3439.64   572.6  3439.4   594.1 3438.65
   611.8  3438.5   661.1  3438.5   684.7 3439.23   694.3 3440.11   706.7 3441.79
   742.7 3447.62   765.5 3450.09   782.7 3451.01   787.7 3451.99   798.7 3452.88
#Mann= 8, -1 ,  0
       0    0.06       0     390    0.08       0  489.56    0.06       0
   509.1   0.045       0   536.8    0.06       0  584.69     0.1       0
  604.69    0.06       0  745.92     0.1       0
Bank Sta=509.1,536.8
XS Rating Curve= 0 ,0
Exp/Cntr(USF)=0,0
Exp/Cntr=0.3,0.1

Type RM Length L Ch R = 1 ,191     ,197.9,191.2,182.2
XS GIS Cut Line= 5
2359471.96275746630507.3660409122360070.69109511630501.523139153
2360115.20026911630494.1049434872360259.11326504630421.406625957
 2360346.6479739630308.650051829
#Sta/Elev= 30
       0 3452.89    80.2 3451.98   139.4  3448.8   155.6 3448.88   176.2 3447.33
     252 3446.27   279.7 3446.67   356.2  3444.3   368.2 3444.91   480.2 3440.74
   532.2 3440.17   556.2 3440.74   632.7 3438.66   645.3 3438.05   651.2 3437.03
   658.4 3435.89   671.9 3435.87   680.63437.045   685.3 3437.98   699.2 3438.12
   710.8  3440.2   721.2 3439.84   734.6 3438.09   792.9 3438.21   803.1 3439.05
   815.5 3437.84   835.8 3438.97   876.3 3442.28   917.2 3449.45   947.9 3452.71
#Mann= 9, -1 ,  0
       0    0.05       0     130    0.06       0     520    0.08       0
  618.76    0.06       0   651.2   0.045       0   680.6    0.06       0
  723.88     0.1       0  803.88    0.06       0  925.11     0.1       0
Bank Sta=651.2,680.6
XS Rating Curve= 0 ,0
Exp/Cntr(USF)=0,0
Exp/Cntr=0.3,0.1

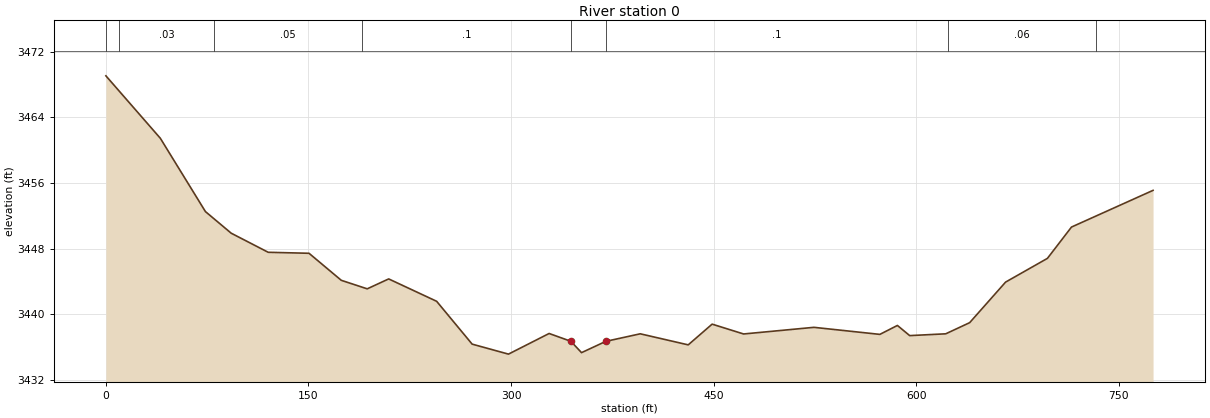
Type RM Length L Ch R = 1 ,0       ,,,
XS GIS Cut Line= 3
2360186.78904024630991.507112601 2360126.8235474630807.554410706
2360378.08603325630282.724748537
#Sta/Elev= 30
       0 3469.08    40.3 3461.46    73.7 3452.51    92.8 3449.87   120.2 3447.54
   150.4 3447.42   174.3 3444.12   193.5 3443.08   209.4 3444.29   244.9 3441.56
   271.2 3436.33   298.1 3435.11   328.2 3437.63   344.33436.677   352.2 3435.29
   370.2 3436.67   395.7 3437.59   431.2 3436.24   448.9 3438.77   472.2 3437.57
   524.3 3438.38   573.1 3437.52   586.1 3438.61   595.2 3437.37   621.9 3437.59
   639.6 3438.95   666.2  3443.9   697.2  3446.8     715 3450.62   775.4  3455.1
#Mann= 8, -1 ,  0
       0    0.05       0      10    0.03       0      80    0.05       0
     190     0.1       0   344.3   0.045       0   370.2     0.1       0
  623.48    0.06       0  733.48     0.1       0
Bank Sta=344.3,370.2
XS Rating Curve= 0 ,0
Exp/Cntr=0.3,0.1
LCMann Table=0

Chan Stop Cuts=-1
Use User Specified Reach Order=0
Composite Channel Slope=5